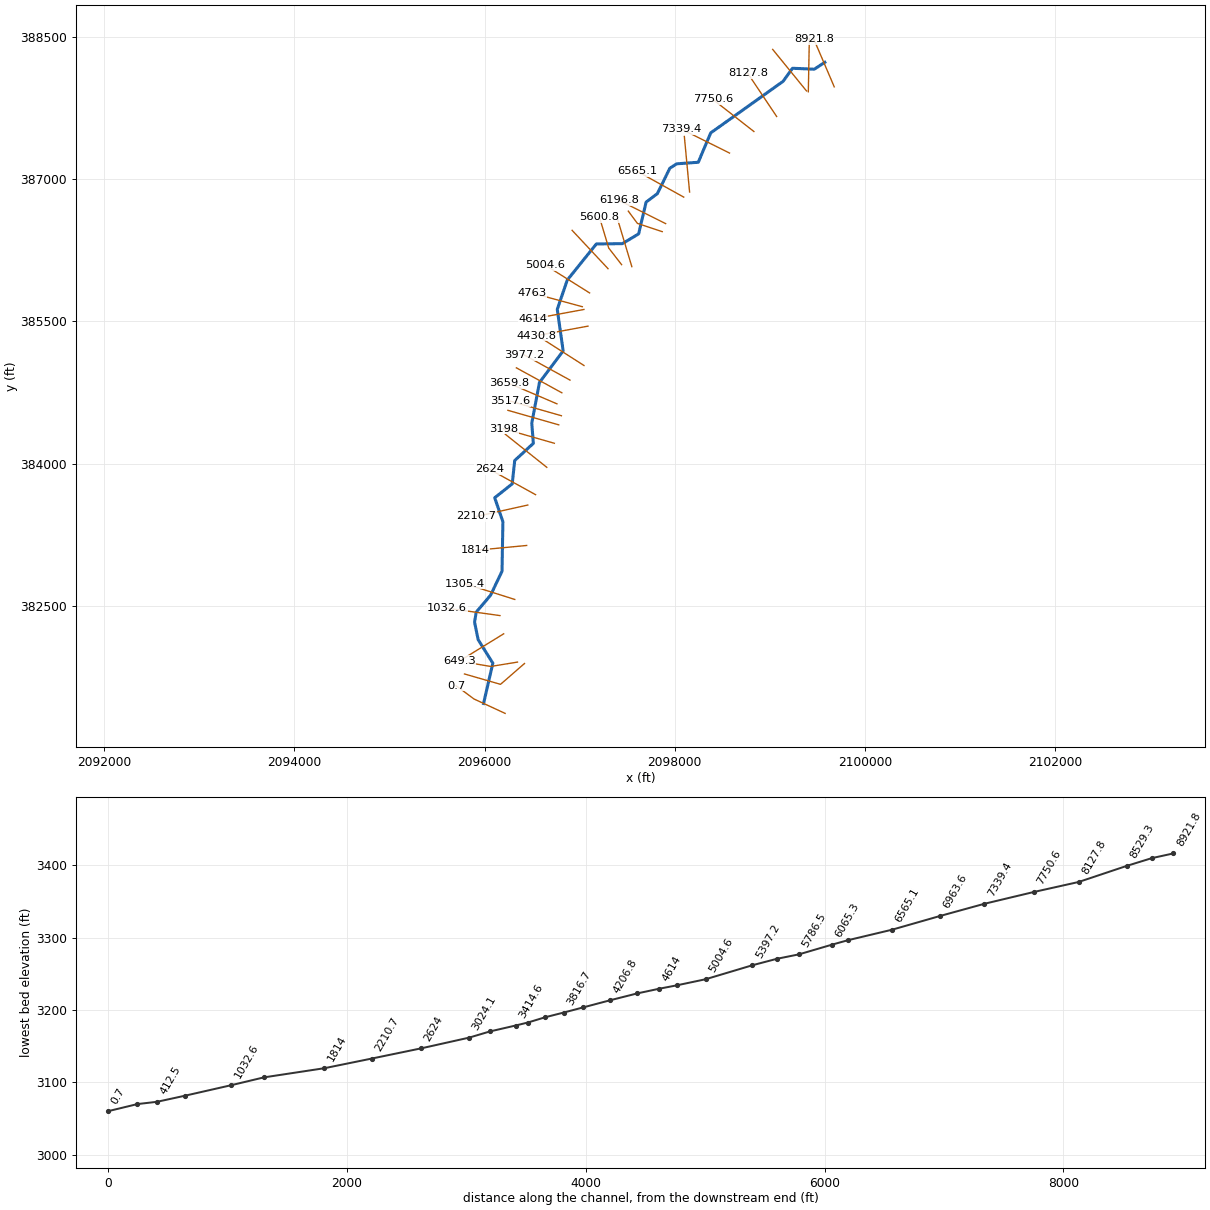
--- JobKnbBr.prj (project) ---

Proj Title=JobKnbBr
Current Plan=p01
Default Exp/Contr=0,0
English Units
Geom File=g01
Flow File=f01
Plan File=p01
BEGIN DESCRIPTION:
END DESCRIPTION:
DSS Export Rating Curves= 0
DSS Export Rating Curve Sorted= 0
DSS Export Volume Flow Curves= 0
DXF OffsetX= 0
DXF OffsetY= 0
DXF ScaleX= 0
DXF ScaleY= 0

--- JobKnbBr.p01 (plan) ---

Plan Title=Floodplain
Program Version=4.00
Geom File=g01
Flow File=f01
K Sum by GR=0
Std Step Tol=0.01
Critical Tol=0.01
Num of Std Step Trials=20
Max Error Tol=0.3
Flow Tol Ratio=0.001
Split Flow NTrial=30
Split Flow Tol=0.02
Split Flow Ratio=0.02
Log Output Level=0
Friction Slope Method=1
Unsteady Friction Slope Method=2
Unsteady Bridges Friction Slope Method=1
Global Log Level=0
CheckData=False
Run HTab=0
Run UNet=0
Run PostProcess=0
UNET Theta=0
UNET Theta Warmup=0
UNET ZTol=0
UNET ZSATol=0
UNET MxIter=0
UNET MaxInSteps=0
UNET DtIC=0
UNET DtMin=0
UNET MaxCRTS=0
UNET WFStab=0
UNET SFStab=0
UNET WFX=0
UNET SFX=0
UNET DSS MLevel=0
UNET DZMax Abort=0
UNET Convert EG Bridges=0
UNET Use Existing IB Tables=0
UNET Froude Limit=0
UNET Froude Power=0
Write IC File=0
Echo Input=False
Echo Output=False
Write Detailed=0

--- JobKnbBr.f01 (steady flow) ---

Flow Title=NFF Regression Equation
Program Version=4.00
Number of Profiles= 1
Profile Names=P100yr
River Rch & RM=JobKnbBr,Main            ,8921.8
 517.107
River Rch & RM=JobKnbBr,Main            ,5786.5
566.1804
River Rch & RM=JobKnbBr,Main            ,5600.8
628.0419
River Rch & RM=JobKnbBr,Main            ,5004.6
631.9794
River Rch & RM=JobKnbBr,Main            ,5004.6
871.4078
River Rch & RM=JobKnbBr,Main            ,248.1
966.3659
River Rch & RM=JobKnbBr,Main            ,0.7
1626.866
Boundary for River Rch & Prof#=JobKnbBr,Main            , 1
Up Type= 0
Dn Type= 1
Dn Known WS=3064.87
DSS Import GetInterval= 0
DSS Import GetPeak= 0
DSS Import FillOption= 0

--- JobKnbBr.g01 (geometry) ---

Geom Title=USGS 10m DEM
Program Version=4.00

River Reach=JobKnbBr        ,Main
Reach XY= 30
     2099579.335      388229.779     2099468.754      388157.274
     2099239.675      388166.873     2099139.852      388028.657
     2098379.046      387485.652     2098248.388      387176.106
     2098020.802      387159.729     2097948.829      387112.764
     2097817.694      386845.239     2097699.703      386756.147
     2097620.886      386421.344     2097450.576      386318.595
     2097176.158      386314.802     2096870.125      385934.157
     2096765.163      385625.595     2096827.129      385188.043
     2096578.003      384855.454     2096497.068      384426.754
     2096513.508      384213.037     2096317.495      384032.199
     2096291.309      383786.237     2096107.064      383640.012
     2096193.337      383387.041     2096184.048      382865.032
     2096063.789       382612.86     2095912.584      382433.648
     2095895.036      382329.828     2095933.055      382144.121
     2096087.355      381896.165     2095989.916      381471.386

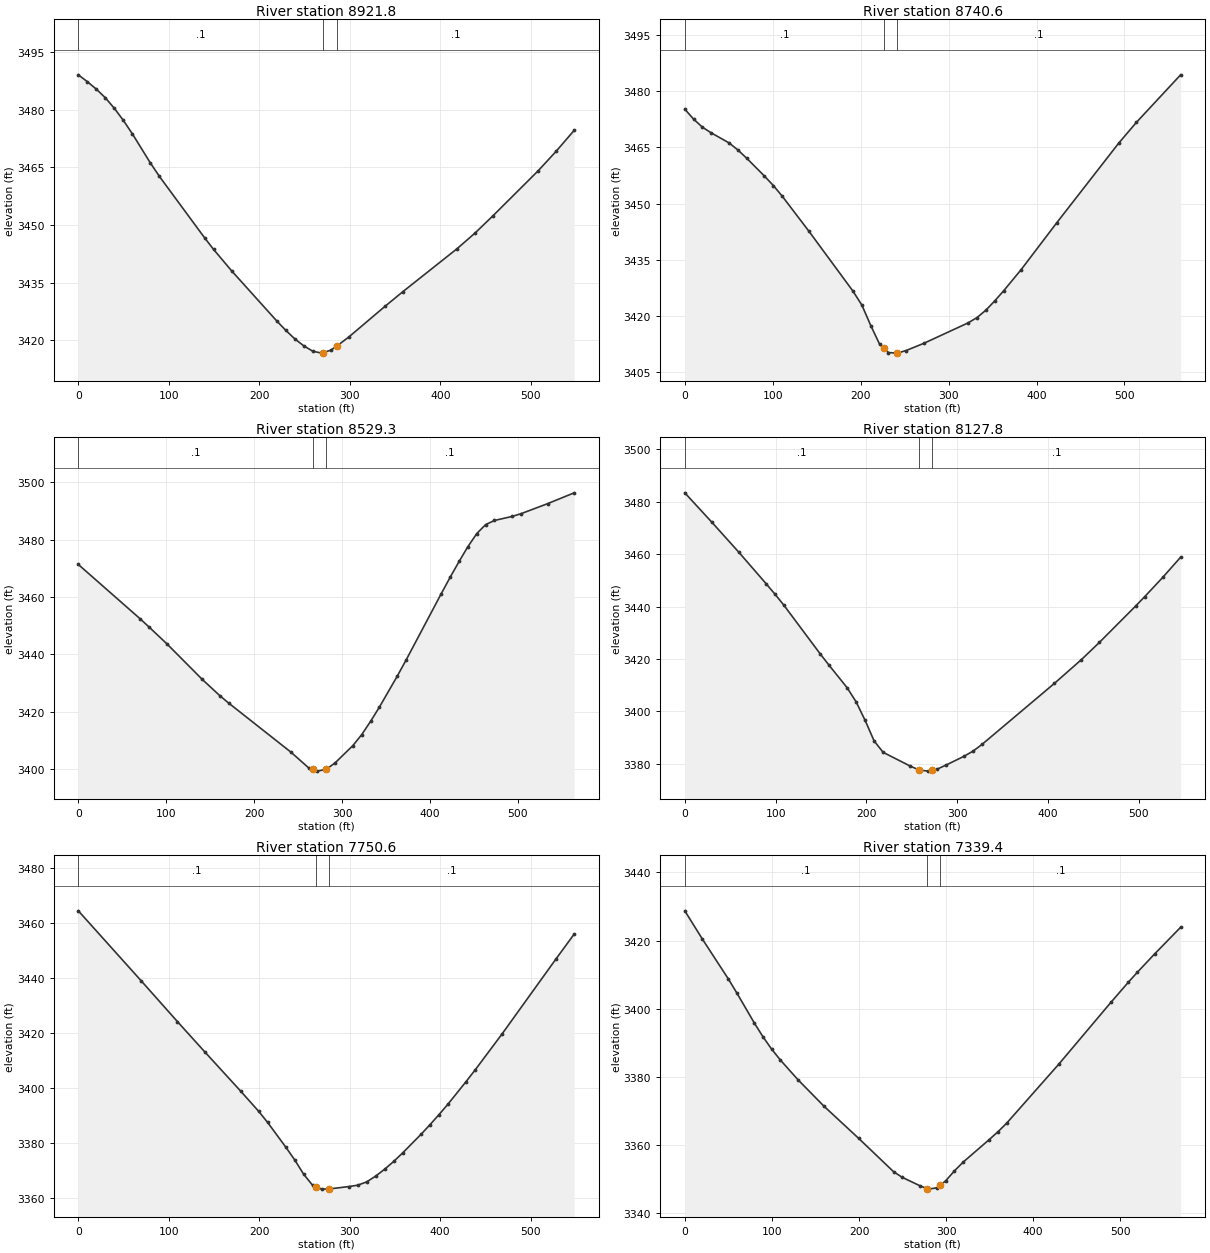
Type RM Length L Ch R = 1 ,8921.8  ,190.7,181.2,171.9
XS GIS Cut Line= 2
     2099678.522      387970.953     2099463.417      388474.743
#Sta/Elev= 30
       0 3489.12      10 3487.33    19.9 3485.39    29.9 3483.13    39.8  3480.4
    49.8 3477.24    59.8 3473.72    79.7 3466.14    89.6 3462.67   139.4 3446.72
   149.4 3443.68   169.3 3438.11   219.1 3425.08   229.1 3422.63     239 3420.41
     249 3418.58     259 3417.17   268.9 3416.67   270.6  3416.8   278.9 3417.44
   285.6 3418.51   298.8 3420.86   338.6 3428.81   358.6 3432.68   418.3 3443.83
   438.2 3447.91   458.2 3452.45     508 3464.13   527.9 3469.22   547.8 3474.66
#Mann= 3 , 0 , 0
       0      .1       0   270.6    .045       0   285.6      .1       0
Bank Sta=270.6,285.6
XS Rating Curve= 0 ,0
Exp/Cntr=0.3,0.1

Type RM Length L Ch R = 1 ,8740.6  ,195.3,211.3,227.2
XS GIS Cut Line= 2
     2099405.835      387918.671     2099416.426      388482.461
#Sta/Elev= 30
       0 3475.21    10.1 3472.54    20.1 3470.39    30.2 3468.87    50.4  3466.2
    60.4 3464.32    70.5  3462.1    90.6 3457.36   100.7 3454.84   110.8    3452
     141  3442.7   191.3 3426.66   201.4 3422.93   211.5 3417.49   221.5 3412.53
   226.6  3411.4   231.6 3410.28   241.6 3410.13   251.7 3410.82   271.9 3412.75
   322.2  3418.2   332.3 3419.61   342.4 3421.58   352.4 3424.04   362.5 3426.72
   382.6 3432.43   422.9 3444.87   493.4 3466.12   513.5 3471.66   563.9 3484.37
#Mann= 3 , 0 , 0
       0      .1       0   226.6    .045       0   241.6      .1       0
Bank Sta=226.6,241.6
XS Rating Curve= 0 ,0
Exp/Cntr=0.3,0.1

Type RM Length L Ch R = 1 ,8529.3  ,403.6,401.5,399.4
XS GIS Cut Line= 2
     2099386.567      387928.197     2099030.904      388365.775
#Sta/Elev= 30
       0 3471.36    70.5 3452.37    80.6 3449.51   100.7  3443.7     141 3431.28
   161.1 3425.58   171.2 3422.99   241.7 3405.96   261.8  3400.5     267 3399.89
   271.9 3399.32     282 3399.96     292 3402.19   312.2 3408.22   322.2 3412.01
   332.3 3416.63   342.4 3421.64   362.5 3432.32   372.6 3437.96   412.8 3461.22
   422.9 3466.92     433  3472.4   443.1  3477.6   453.1 3482.12   463.2 3485.26
   473.3 3486.71   493.4 3488.11   503.5 3489.07   533.7 3492.56   563.9 3496.34
#Mann= 3 , 0 , 0
       0      .1       0     267    .045       0     282      .1       0
Bank Sta=267,282
XS Rating Curve= 0 ,0
Exp/Cntr=0.3,0.1

Type RM Length L Ch R = 1 ,8127.8  ,370.1,377.2,384.4
XS GIS Cut Line= 2
     2099072.472      387658.924     2098769.355      388113.056
#Sta/Elev= 30
       0 3483.41    29.8 3472.18    59.6 3460.69    89.4 3448.77    99.3 3444.72
   109.2 3440.46   148.9 3422.01   158.8 3417.61   178.7 3409.01   188.6 3403.63
   198.6  3396.5   208.5 3388.66   218.4 3384.32   248.2 3379.07   257.4 3377.67
   258.1 3377.56     268 3377.14   272.4 3377.48     278 3377.91   287.9 3379.49
   307.8 3382.87   317.7 3384.84   327.6 3387.43     407 3410.64   436.8 3419.74
   456.6 3426.31   496.4 3440.16   506.3 3443.71   526.2 3451.08     546 3458.83
#Mann= 3 , 0 , 0
       0      .1       0   257.4    .045       0   272.4      .1       0
Bank Sta=257.4,272.4
XS Rating Curve= 0 ,0
Exp/Cntr=0.3,0.1

Type RM Length L Ch R = 1 ,7750.6  ,406.4,411.2,416
XS GIS Cut Line= 2
     2098833.272      387500.409     2098401.982      387838.601
#Sta/Elev= 30
       0 3464.37    69.8 3438.82   109.6 3424.09   139.5 3413.21   179.4 3398.86
   199.3 3391.53   209.3 3387.44   229.2 3378.54   239.2 3373.84   249.1 3368.64
   259.1 3364.56   262.5  3364.1     269 3363.22   277.5 3363.29     299 3364.15
   308.9 3364.65   318.9 3365.88   328.8 3367.98   338.8 3370.51   348.8 3373.34
   358.7 3376.44   378.7  3383.1   388.6 3386.59   398.6 3390.27   408.6  3394.1
   428.5 3402.25   438.5 3406.48   468.4 3419.62   528.1 3446.92   548.1 3455.91
#Mann= 3 , 0 , 0
       0      .1       0   262.5    .045       0   277.5      .1       0
Bank Sta=262.5,277.5
XS Rating Curve= 0 ,0
Exp/Cntr=0.3,0.1

Type RM Length L Ch R = 1 ,7339.4  ,399,375.8,352.7
XS GIS Cut Line= 2
     2098576.735       387273.53     2098067.196      387527.302
#Sta/Elev= 30
       0 3428.72      20  3420.5    49.9 3408.76    59.9 3404.54    79.9 3395.75
    89.9 3391.68    99.9 3388.05   109.8  3384.9   129.8 3379.17   159.8 3371.36
   199.7  3361.9   239.7 3352.13   249.7 3350.47   269.6 3348.05   278.1 3347.17
   279.6 3347.02   289.6 3347.41   293.1 3348.14   299.6 3349.49   309.6  3352.4
   319.6 3354.96   349.5 3361.57   359.5 3363.86   369.5 3366.38   429.4 3383.72
   489.3 3401.89   509.3 3407.79   519.3 3410.62   539.3 3416.05   569.2 3423.89
#Mann= 3 , 0 , 0
       0      .1       0   278.1    .045       0   293.1      .1       0
Bank Sta=278.1,293.1
XS Rating Curve= 0 ,0
Exp/Cntr=0.3,0.1

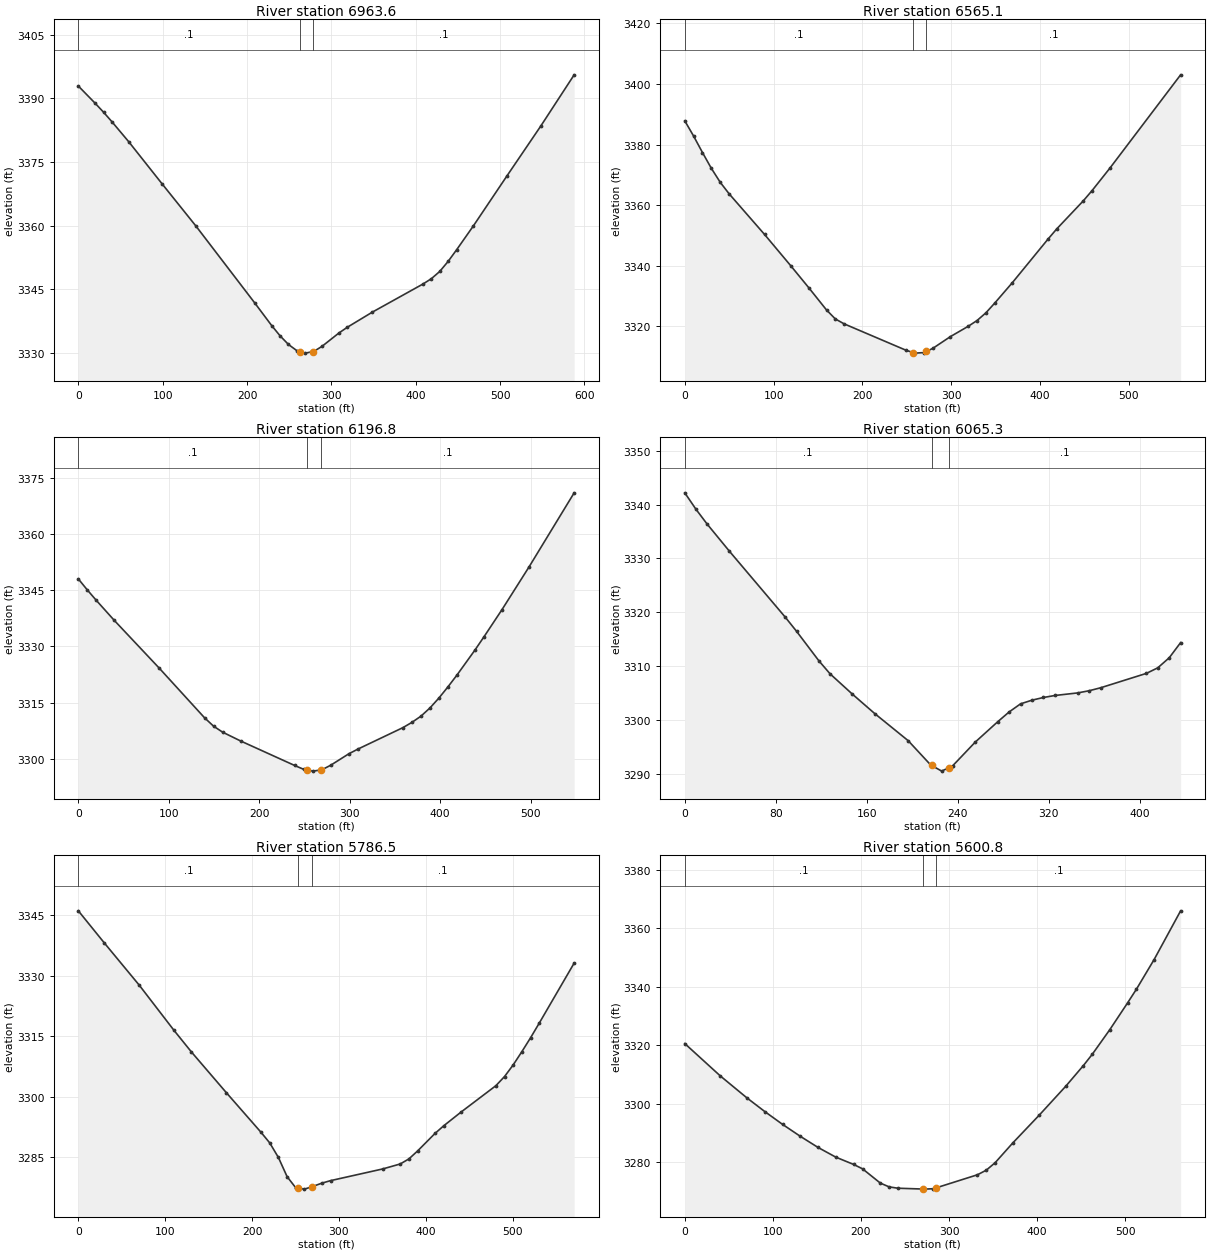
Type RM Length L Ch R = 1 ,6963.6  ,375.7,398.4,421.2
XS GIS Cut Line= 2
     2098156.919      386862.364     2098101.919      387447.624
#Sta/Elev= 29
       0 3392.89    19.9 3388.84    29.9 3386.72    39.8 3384.48    59.8 3379.75
    99.6 3369.76   139.5 3359.87   209.2 3341.75   229.2 3336.44   239.1 3334.03
   249.1 3331.98     259 3330.53   262.9  3330.3     269 3329.94   277.9 3330.28
     279 3330.32   288.9 3331.54   308.9 3334.68   318.8 3336.03   348.7 3339.62
   408.5 3346.22   418.5 3347.48   428.4 3349.18   438.4 3351.56   448.4 3354.28
   468.3 3359.92   508.1  3371.7     548 3383.39   587.8 3395.53
#Mann= 3 , 0 , 0
       0      .1       0   262.9    .045       0   277.9      .1       0
Bank Sta=262.9,277.9
XS Rating Curve= 0 ,0
Exp/Cntr=0.3,0.1

Type RM Length L Ch R = 1 ,6565.1  ,367.6,368.4,369.1
XS GIS Cut Line= 2
     2098095.182      386808.982     2097607.142       387080.42
#Sta/Elev= 30
       0 3387.84      10 3382.77    19.9 3377.37    29.9 3372.15    39.9 3367.54
    49.9 3363.74    89.8 3350.32   119.7 3339.84   139.6 3332.72   159.6 3325.37
   169.5 3322.41   179.5 3320.77   249.3 3312.04   257.2 3311.31   259.3 3311.11
   269.2 3311.29   272.2 3311.69   279.2 3312.66   299.2 3316.58   319.1 3319.96
   329.1 3321.87   339.1 3324.42     349 3327.62     369 3334.42   408.9 3348.72
   418.8 3352.12   448.8 3361.42   458.7 3364.81   478.7  3372.2   558.4 3403.04
#Mann= 3 , 0 , 0
       0      .1       0   257.2    .045       0   272.2      .1       0
Bank Sta=257.2,272.2
XS Rating Curve= 0 ,0
Exp/Cntr=0.3,0.1

Type RM Length L Ch R = 1 ,6196.8  ,128.2,131.4,134.7
XS GIS Cut Line= 2
        2097905.      386529.698     2097414.897      386774.842
#Sta/Elev= 30
       0 3348.09      10 3345.12    19.9 3342.34    39.8 3336.97    89.7 3324.13
   139.5 3310.91   149.4 3308.68   159.4 3307.07   179.3 3304.71   239.1 3298.14
   249.1 3297.11   252.9 3296.93     259 3296.63   267.9 3296.93     269 3296.97
     279 3298.22   298.9 3301.26   308.9 3302.52   358.7 3308.27   368.6 3309.67
   378.6 3311.33   388.6 3313.54   398.5 3316.19   408.5 3319.19   418.5 3322.36
   438.4 3329.06   448.4 3332.62   468.3 3339.89   498.2 3351.33     548 3371.14
#Mann= 3 , 0 , 0
       0      .1       0   252.9    .045       0   267.9      .1       0
Bank Sta=252.9,267.9
XS Rating Curve= 0 ,0
Exp/Cntr=0.3,0.1

Type RM Length L Ch R = 1 ,6065.3  ,300.5,278.8,257.1
XS GIS Cut Line= 3
     2097869.241      386444.796     2097608.193      386531.742
     2097512.261      386661.031
#Sta/Elev= 30
       0 3342.17     9.8 3339.13    19.6 3336.39    39.3 3331.33    88.4 3319.11
    98.3  3316.5   117.9 3311.04   127.8 3308.61   147.4 3304.85     167 3301.26
   196.5 3296.22   216.2 3291.74   217.1 3291.63     226 3290.58   232.1 3291.22
   235.8 3291.61   255.5 3295.97   275.2 3299.73   285.2 3301.54   295.3 3303.05
   305.3 3303.73   315.4 3304.23   325.5  3304.6   345.6 3305.08   355.6 3305.48
   365.7 3306.03     406  3308.7     416 3309.73   426.1  3311.6   436.1 3314.41
#Mann= 3 , 0 , 0
       0      .1       0   217.1    .045       0   232.1      .1       0
Bank Sta=217.1,232.1
XS Rating Curve= 0 ,0
Exp/Cntr=0.3,0.1

Type RM Length L Ch R = 1 ,5786.5  ,185.6,185.8,186
XS GIS Cut Line= 2
     2097549.623      386075.517     2097385.772      386622.209
#Sta/Elev= 30
       0  3346.1      30 3338.11    70.1 3327.66   110.1 3316.45   130.2 3311.08
   170.2 3301.03   210.3 3291.15   220.3 3288.53   230.3 3284.91   240.3 3280.15
   250.3 3277.38   253.4 3277.28   260.3 3277.06   268.4 3277.62   280.4 3278.55
   290.4 3279.17   350.4 3282.07   370.5  3283.3   380.5 3284.56   390.5 3286.53
   410.5 3290.87   420.5 3292.76   440.6 3296.19   480.6 3302.72   490.6    3305
   500.6  3307.9   510.6 3311.19   520.7 3314.67   530.7 3318.31   570.7 3333.14
#Mann= 3 , 0 , 0
       0      .1       0   253.4    .045       0   268.4      .1       0
Bank Sta=253.4,268.4
XS Rating Curve= 0 ,0
Exp/Cntr=0.3,0.1

Type RM Length L Ch R = 1 ,5600.8  ,193.3,203.6,214
XS GIS Cut Line= 3
     2097441.889      386096.772     2097306.169      386272.419
     2097208.271      386599.057
#Sta/Elev= 30
       0 3320.63    40.4 3309.55    70.6 3302.05    90.8  3297.4     111 3293.01
   131.2 3288.92   151.3 3285.12   171.5  3281.8   191.7 3279.31   201.8 3277.82
     222 3272.94     232 3271.64     242 3271.18   270.1  3270.9   272.1 3270.87
   282.2 3271.01   285.1 3271.28   332.3 3275.78   342.3 3277.34   352.4 3279.91
   372.4 3286.65   402.5 3296.18   432.6 3306.06   452.6 3313.12   462.7 3316.98
   482.7 3325.44   502.8 3334.56   512.8 3339.22   532.9 3349.36     563 3366.02
#Mann= 3 , 0 , 0
       0      .1       0   270.1    .045       0   285.1      .1       0
Bank Sta=270.1,285.1
XS Rating Curve= 0 ,0
Exp/Cntr=0.3,0.1

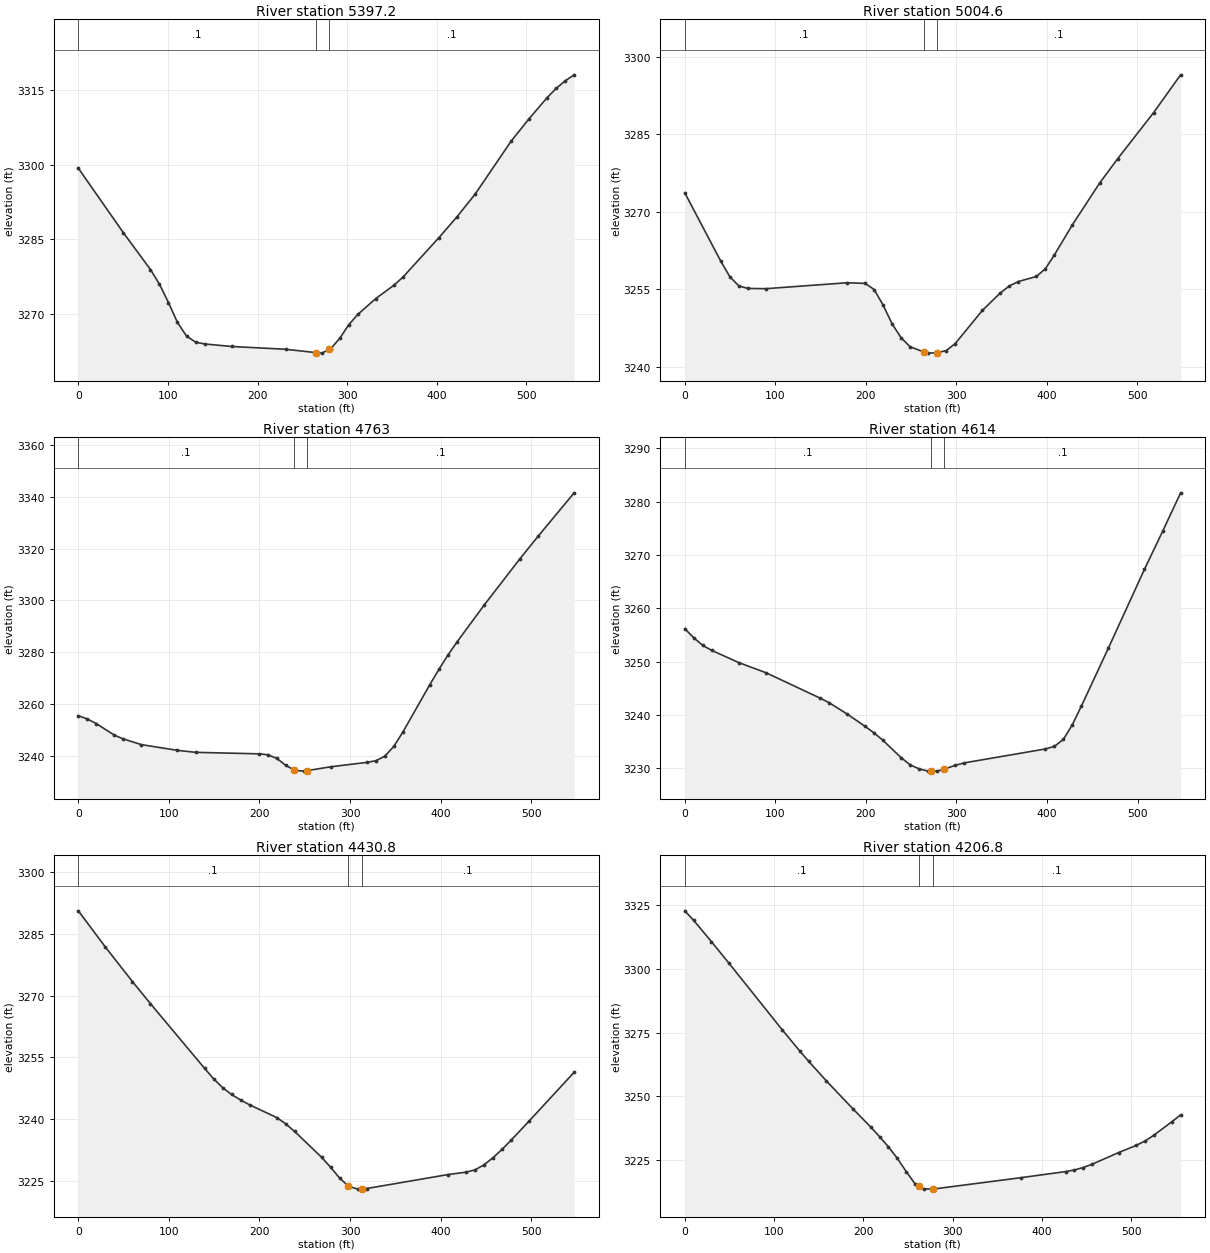
Type RM Length L Ch R = 1 ,5397.2  ,386.7,392.5,398.4
XS GIS Cut Line= 2
     2097298.998      386054.762      2096921.25      386458.899
#Sta/Elev= 30
       0 3299.32    50.3 3286.29    80.5 3278.87    90.5 3275.92   100.6  3272.2
   110.6  3268.2   120.7 3265.46   130.8 3264.23   140.8 3263.86     171 3263.35
   231.3 3262.79   265.2 3262.11   271.6 3262.01   280.2 3262.77   281.6 3262.89
   291.7    3265   301.7 3267.73   311.8 3269.81   331.9 3273.03     352 3275.69
   362.1 3277.33   402.3 3285.31   422.4  3289.5   442.6 3294.06   482.8 3304.76
   502.9  3309.3     523 3313.55   533.1 3315.41   543.1 3316.94   553.2 3318.16
#Mann= 3 , 0 , 0
       0      .1       0   265.2    .045       0   280.2      .1       0
Bank Sta=265.2,280.2
XS Rating Curve= 0 ,0
Exp/Cntr=0.3,0.1

Type RM Length L Ch R = 1 ,5004.6  ,235,241.6,248.3
XS GIS Cut Line= 2
     2097105.329      385798.897     2096641.519      386090.466
#Sta/Elev= 30
       0 3273.67    39.8 3260.42    49.8 3257.42    59.8 3255.64    69.7 3255.16
    89.6 3255.11   179.3 3256.26   199.2 3256.14   209.2 3254.95   219.1 3251.93
   229.1 3248.28   239.1 3245.58     249 3243.85   263.9 3242.87   268.9 3242.63
   278.9 3242.71   288.9 3243.13   298.8 3244.49   328.7 3250.89   348.6 3254.29
   358.6 3255.65   368.6  3256.5   388.5 3257.48   398.4 3258.98   408.4 3261.67
   428.3  3267.5   458.2 3275.53   478.1 3280.25     518 3289.22   547.8 3296.53
#Mann= 3 , 0 , 0
       0      .1       0   263.9    .045       0   278.9      .1       0
Bank Sta=263.9,278.9
XS Rating Curve= 0 ,0
Exp/Cntr=0.3,0.1

Type RM Length L Ch R = 1 ,4763    ,138.8,149,159.1
XS GIS Cut Line= 2
     2097028.781      385653.695     2096500.562       385797.57
#Sta/Elev= 30
       0 3255.57      10 3254.29    19.9 3252.51    39.8 3248.06    49.8 3246.59
    69.7  3244.4   109.5  3242.2   129.4 3241.44   199.1 3240.86     209 3240.52
     219 3239.14   228.9 3236.45     238 3234.69   238.9 3234.52   248.8 3234.19
     253 3234.41   278.7 3235.86   318.5 3237.56   328.5  3238.2   338.4 3239.94
   348.4 3243.75   358.3 3249.21   388.2 3267.59   398.2 3273.45   408.1 3278.93
   418.1 3283.98   447.9 3298.12   487.7 3316.12   507.6 3324.73   547.5 3341.51
#Mann= 3 , 0 , 0
       0      .1       0     238    .045       0     253      .1       0
Bank Sta=238,253
XS Rating Curve= 0 ,0
Exp/Cntr=0.3,0.1

Type RM Length L Ch R = 1 ,4614    ,183.1,183.1,183.1
XS GIS Cut Line= 2
     2097045.845      385624.546      2096507.52      385524.942
#Sta/Elev= 30
       0 3256.18      10 3254.46    19.9 3253.03    29.9  3252.1    59.7 3249.81
    89.6 3247.92   149.3 3243.16   159.3  3242.3   179.2 3240.17   199.1 3237.85
     209 3236.62     219  3235.2   238.9 3231.97   248.8 3230.64   258.8 3229.86
   268.8 3229.45   271.6 3229.45   278.7 3229.46   286.6 3229.84   298.6 3230.53
   308.6    3231   398.2 3233.61   408.1 3234.09   418.1 3235.42     428 3238.18
     438 3241.69   467.8 3252.56   507.6 3267.34   527.6 3274.45   547.5 3281.68
#Mann= 3 , 0 , 0
       0      .1       0   271.6    .045       0   286.6      .1       0
Bank Sta=271.6,286.6
XS Rating Curve= 0 ,0
Exp/Cntr=0.3,0.1

Type RM Length L Ch R = 1 ,4430.8  ,241.5,224,206.6
XS GIS Cut Line= 2
     2097088.772      385448.924     2096550.447       385349.32
#Sta/Elev= 30
       0 3290.67    29.9 3281.85    59.7 3273.48    79.6  3268.1   139.4 3252.36
   149.3 3249.83   159.3 3247.67   169.2    3246   179.2 3244.66   189.1 3243.48
     219  3240.4   228.9 3238.88   238.9    3237   268.8 3230.69   278.7 3228.26
   288.7 3225.62   297.9  3223.8   298.6 3223.66   308.6 3222.98   312.9 3223.05
   318.5 3223.13   408.1 3226.52     428  3227.1     438 3227.67   447.9 3228.88
   457.9 3230.62   467.8 3232.64   477.8 3234.86   497.7 3239.52   547.5 3251.41
#Mann= 3 , 0 , 0
       0      .1       0   297.9    .045       0   312.9      .1       0
Bank Sta=297.9,312.9
XS Rating Curve= 0 ,0
Exp/Cntr=0.3,0.1

Type RM Length L Ch R = 1 ,4206.8  ,228.1,229.6,231.1
XS GIS Cut Line= 2
     2097046.434      385033.782     2096578.965      385333.764
#Sta/Elev= 30
       0 3322.74     9.9 3319.03    29.8 3310.68    49.6 3302.15   109.1 3276.11
   128.9 3267.73   138.9 3263.69   158.7 3256.03   188.4 3245.08   208.3 3237.97
   218.2 3234.19   228.1 3230.22     238 3225.73     248 3220.53   257.9 3215.73
   262.9 3214.73   267.8 3213.74   277.7 3213.63   277.9 3213.64   376.9 3218.14
   426.5  3220.5   436.4 3221.13   446.3  3222.1   456.3  3223.4     486 3227.98
   505.8 3230.79   515.8 3232.56   525.7 3234.84   545.5 3240.03   555.4 3242.74
#Mann= 3 , 0 , 0
       0      .1       0   262.9    .045       0   277.9      .1       0
Bank Sta=262.9,277.9
XS Rating Curve= 0 ,0
Exp/Cntr=0.3,0.1

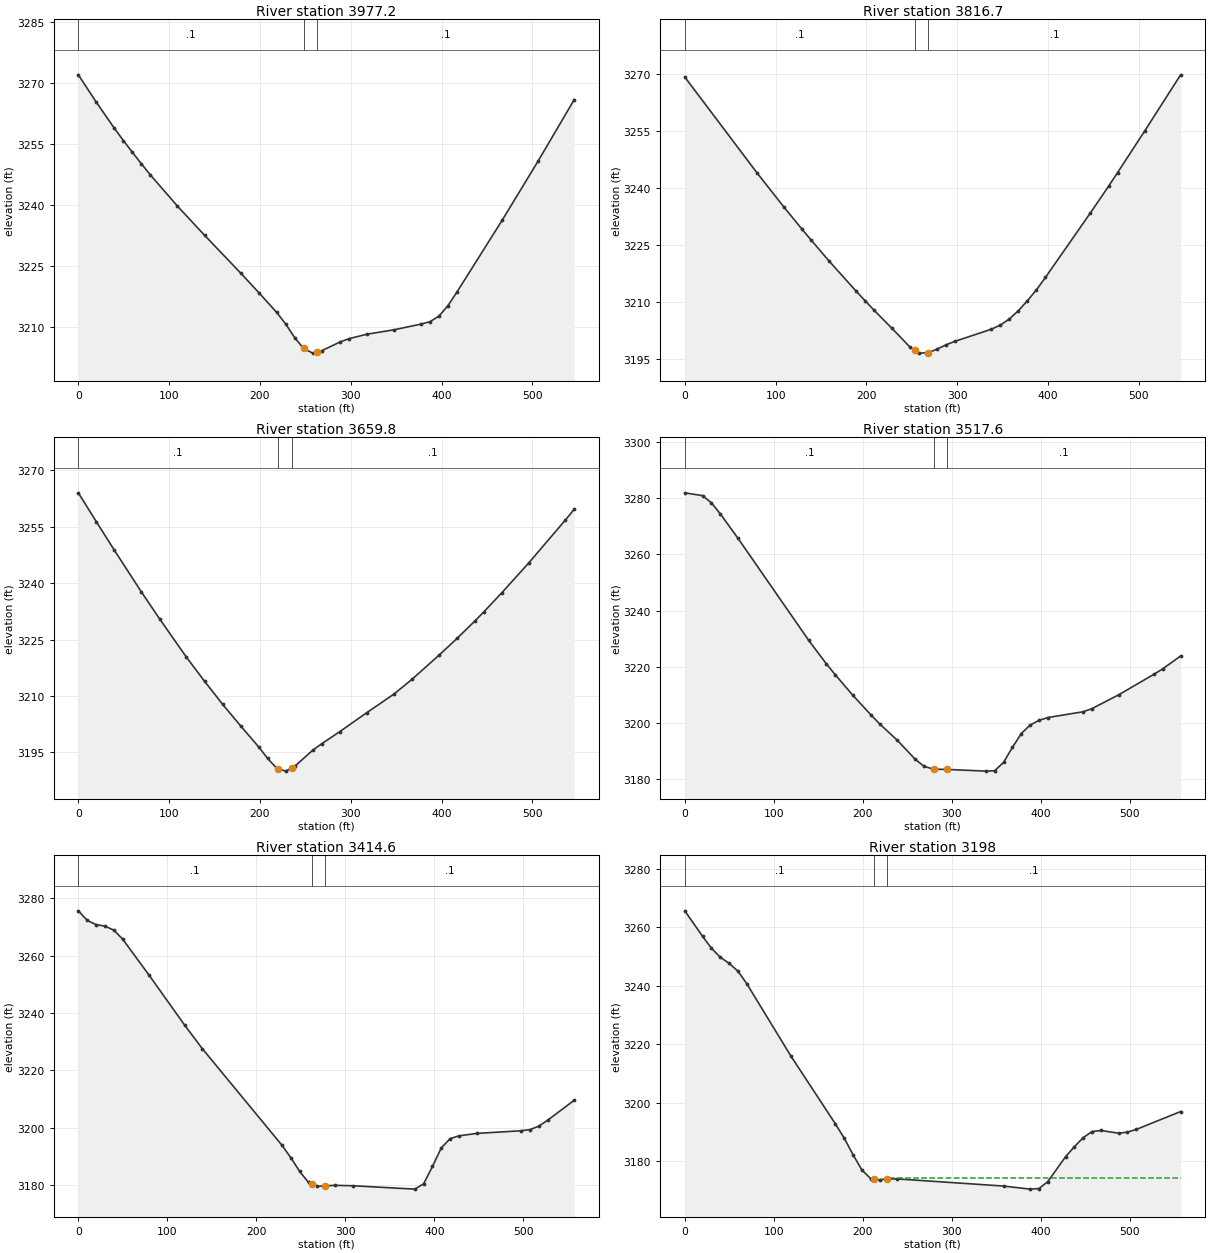
Type RM Length L Ch R = 1 ,3977.2  ,160.6,160.5,160.5
XS GIS Cut Line= 2
     2096899.009      384880.111     2096420.595      385143.239
#Sta/Elev= 30
       0 3272.04    19.8  3265.3    39.7 3258.89    49.6 3255.87    59.6 3252.97
    69.5 3250.14    79.4 3247.41   109.2 3239.74     139 3232.58   178.7  3223.3
   198.6  3218.5   218.4 3213.62   228.3 3210.77   238.2 3207.43     248 3204.73
   258.1 3203.59     263 3203.88     268 3204.18   287.9  3206.3   297.8 3207.13
   317.7 3208.24   347.4 3209.32   377.2 3210.72   387.2 3211.32   397.1 3212.68
     407 3215.26     417 3218.64   466.6 3236.22   506.3 3250.83     546 3265.91
#Mann= 3 , 0 , 0
       0      .1       0     248    .045       0     263      .1       0
Bank Sta=248,263
XS Rating Curve= 0 ,0
Exp/Cntr=0.3,0.1

Type RM Length L Ch R = 1 ,3816.7  ,154.7,156.9,159.1
XS GIS Cut Line= 2
     2096813.718      384746.115     2096335.304      385009.243
#Sta/Elev= 29
       0 3269.11    79.4 3243.98   109.2 3234.94     129 3229.16     139 3226.32
   158.8 3220.79   188.6 3212.88   198.6 3210.33   208.5 3207.83   228.3 3203.05
   248.2  3198.1   253.1 3197.34   258.1 3196.57   268.1 3196.67     278 3197.65
   287.9 3198.77   297.8  3199.7   337.5 3202.85   347.4 3203.93   357.4 3205.55
   367.3 3207.71   377.2 3210.32   387.2 3213.18   397.1 3216.46   446.7 3233.43
   466.6 3240.41   476.5 3243.98   506.3 3254.89     546  3269.7
#Mann= 3 , 0 , 0
       0      .1       0   253.1    .045       0   268.1      .1       0
Bank Sta=253.1,268.1
XS Rating Curve= 0 ,0
Exp/Cntr=0.3,0.1

Type RM Length L Ch R = 1 ,3659.8  ,139.3,142.2,145.1
XS GIS Cut Line= 2
     2096761.772      384629.923      2096259.95      384845.076
#Sta/Elev= 30
       0 3264.03    19.8 3256.35    39.7 3248.76    69.5 3237.64    89.4 3230.54
   119.1 3220.28     139  3213.9   158.8  3207.8   178.7 3202.04   198.6 3196.43
   208.5 3193.36   218.4 3190.77     220 3190.64   228.3 3189.99     235 3190.83
   238.2 3191.24   258.1 3195.55     268 3197.27   287.9  3200.5   317.7 3205.55
   347.4 3210.46   367.3 3214.39   397.1 3220.81     417 3225.29   436.8 3229.96
   446.7  3232.4   466.6 3237.51   496.4 3245.49   536.1 3256.73     546 3259.64
#Mann= 3 , 0 , 0
       0      .1       0     220    .045       0     235      .1       0
Bank Sta=220,235
XS Rating Curve= 0 ,0
Exp/Cntr=0.3,0.1

Type RM Length L Ch R = 1 ,3517.6  ,104,103,114.6
XS GIS Cut Line= 2
     2096808.541      384504.478     2096273.089       384657.87
#Sta/Elev= 30
       0 3281.96    19.9 3280.96    29.8 3278.45    39.8  3274.5    59.7 3265.79
   139.2  3229.4   159.1 3221.02   169.1 3217.12     189 3209.76   208.9 3202.92
   218.8 3199.68   238.7 3193.82   258.6 3187.12   268.6 3184.55   279.7 3183.48
   294.7 3183.42   338.2 3182.81   348.1 3182.95   358.1 3185.94     368 3191.24
     378 3196.19   387.9 3199.22   397.8 3200.87   407.8  3201.9   447.6 3203.97
   457.5 3205.09   487.4    3210   527.2 3217.34   537.1  3219.3     557 3223.83
#Mann= 3 , 0 , 0
       0      .1       0   279.7    .045       0   294.7      .1       0
Bank Sta=279.7,294.7
XS Rating Curve= 0 ,0
Exp/Cntr=0.3,0.1

Type RM Length L Ch R = 1 ,3414.6  ,216.3,216.5,216.8
XS GIS Cut Line= 2
     2096781.002      384408.344      2096245.55      384561.737
#Sta/Elev= 30
       0 3275.57      10 3272.25    19.9 3270.77    29.8 3270.25    39.8 3268.86
    49.7 3265.75    79.6 3253.12   119.4 3235.79   139.2 3227.61   228.8 3193.93
   238.7 3189.61   248.7 3184.81   258.6    3181     262 3180.54   268.6 3179.65
     277  3179.8   288.4 3179.99   308.3 3179.85     378 3178.67   387.9 3180.53
   397.8 3186.56   407.8 3193.06   417.7 3196.27   427.7 3197.22   447.6 3198.07
   497.3 3198.99   507.3 3199.38   517.2 3200.59   527.2 3202.65     557  3209.6
#Mann= 3 , 0 , 0
       0      .1       0     262    .045       0     277      .1       0
Bank Sta=262,277
XS Rating Curve= 0 ,0
Exp/Cntr=0.3,0.1

Type RM Length L Ch R = 1 ,3198    ,182.8,173.9,165
XS GIS Cut Line= 2
     2096734.639      384214.131     2096199.187      384367.523
#Sta/Elev= 30
       0  3265.6    19.9 3256.91    29.8 3252.86    39.8 3249.74    49.7 3247.67
    59.7 3244.96    69.6 3240.68   119.4 3215.82   169.1 3192.77     179 3187.86
     189 3182.19   198.9 3176.97   208.9 3173.97   212.3 3173.84   218.8  3173.6
   227.3 3173.89   238.7  3173.9   358.1 3171.45   387.9  3170.4   397.8 3170.59
   407.8 3172.97   427.7 3181.47   437.6  3184.9   447.6 3188.01   457.5  3190.1
   467.5 3190.46   487.4 3189.53   497.3  3189.9   507.3 3190.84     557 3196.94
#Mann= 3 , 0 , 0
       0      .1       0   212.3    .045       0   227.3      .1       0
#XS Ineff= 2 , 0
                          230.65         3174.05
Permanent Ineff=
       F       F
Bank Sta=212.3,227.3
XS Rating Curve= 0 ,0
Exp/Cntr=0.3,0.1

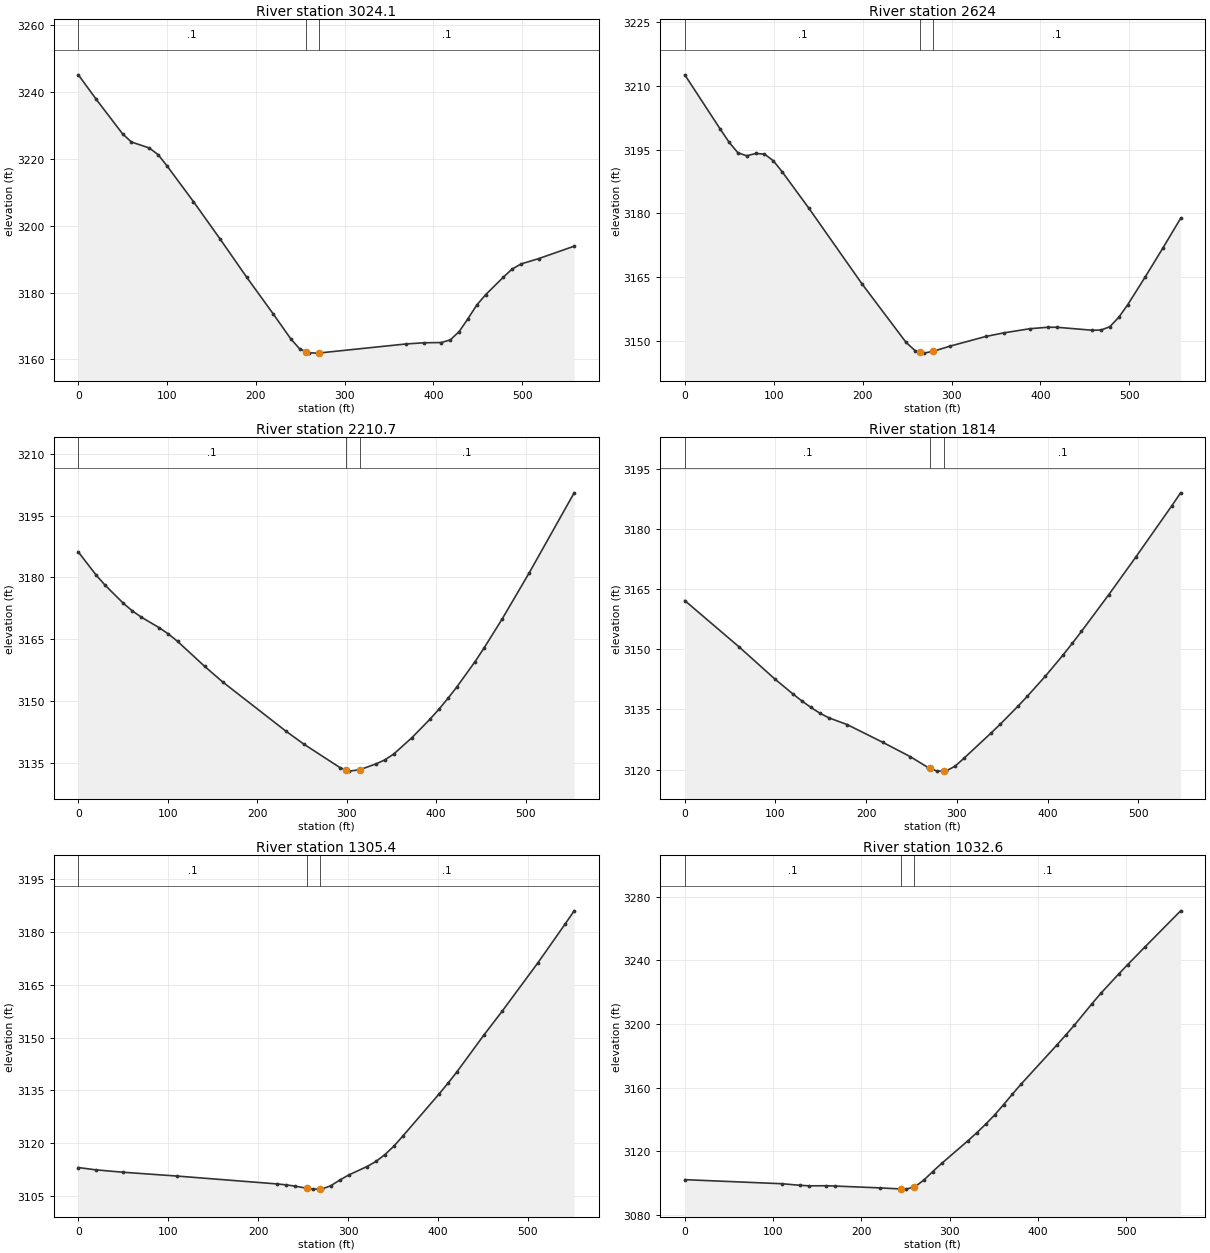
Type RM Length L Ch R = 1 ,3024.1  ,394.5,400.1,405.5
XS GIS Cut Line= 2
     2096654.801      383960.694     2096218.496        384309.4
#Sta/Elev= 30
       0 3245.18      20 3237.91    49.9 3227.49    59.8 3225.07    79.8 3223.29
    89.8 3221.31    99.7 3217.99   129.7 3207.22   159.6 3196.06   189.5 3184.64
   219.4 3173.65   239.4  3166.1   249.3 3163.14   256.5  3162.3   259.3 3161.97
   269.3 3161.86   271.5 3161.91     369  3164.6     389 3164.96   408.9 3165.03
   418.9 3165.82   428.9 3168.29   438.8 3172.14   448.8 3176.26   458.8 3179.36
   478.7 3184.59   488.7 3187.04   498.7 3188.56   518.6 3190.16   558.5 3193.88
#Mann= 3 , 0 , 0
       0      .1       0   256.5    .045       0   271.5      .1       0
Bank Sta=256.5,271.5
XS Rating Curve= 0 ,0
Exp/Cntr=0.3,0.1

Type RM Length L Ch R = 1 ,2624    ,395.8,413.2,430.6
XS GIS Cut Line= 2
     2096536.983      383672.537     2096048.733      383941.854
#Sta/Elev= 30
       0 3212.58    39.8 3199.83    49.8 3196.73    59.7 3194.23    69.7 3193.53
    79.7 3194.07    89.6 3193.93    99.6 3192.35   109.5 3189.77   139.4 3181.23
   199.1 3163.44   248.9  3149.6   258.9  3147.7   264.2 3147.38   268.8 3147.09
   279.2 3147.51   298.7 3148.76   338.5 3151.01   358.5 3151.85   388.3 3152.84
   408.2 3153.18   418.2 3153.18     458 3152.48     468 3152.52   477.9  3153.3
   487.9 3155.48   497.9 3158.42   517.8 3165.03   537.7 3171.84   557.6 3178.82
#Mann= 3 , 0 , 0
       0      .1       0   264.2    .045       0   279.2      .1       0
Bank Sta=264.2,279.2
XS Rating Curve= 0 ,0
Exp/Cntr=0.3,0.1

Type RM Length L Ch R = 1 ,2210.7  ,398.8,396.7,394.7
XS GIS Cut Line= 2
     2096455.417      383563.164     2095914.367      383442.668
#Sta/Elev= 30
       0 3186.19    20.2 3180.51    30.2 3178.07    50.4 3173.72    60.5 3171.87
    70.6 3170.35    90.7 3167.77   100.8 3166.27   110.9  3164.5   141.1 3158.45
   161.2 3154.67   231.8 3142.74     252 3139.56   292.3 3133.87   299.4 3133.25
   302.4 3132.99   314.4 3133.31   332.6 3134.73   342.7 3135.72   352.7 3137.16
   372.9 3141.11     393 3145.57   403.1 3148.01   413.2 3150.65   423.3 3153.47
   443.4 3159.54   453.5 3162.86   473.7 3169.89   503.9 3181.07   554.3 3200.55
#Mann= 3 , 0 , 0
       0      .1       0   299.4    .045       0   314.4      .1       0
Bank Sta=299.4,314.4
XS Rating Curve= 0 ,0
Exp/Cntr=0.3,0.1

Type RM Length L Ch R = 1 ,1814    ,517.8,508.6,499.3
XS GIS Cut Line= 2
     2096443.542      383136.904      2095899.31      383085.103
#Sta/Elev= 30
       0 3162.16    59.6 3150.66    99.4 3142.58   119.3 3138.86   129.2 3137.11
   139.2  3135.5   149.1 3134.06     159 3132.91   178.9 3131.25   218.7 3126.77
   248.5 3123.25   268.4 3120.51   270.8 3120.29   278.3 3119.63   285.8 3119.68
   288.3 3119.69   298.2 3120.89   308.1  3122.9     338  3129.2   347.9 3131.35
   367.8 3135.92   377.7 3138.31   397.6 3143.32   417.5 3148.71   427.4 3151.55
   437.4 3154.49   467.2 3163.55     497 3172.92   536.8 3185.75   546.7 3189.03
#Mann= 3 , 0 , 0
       0      .1       0   270.8    .045       0   285.8      .1       0
Bank Sta=270.8,285.8
XS Rating Curve= 0 ,0
Exp/Cntr=0.3,0.1

Type RM Length L Ch R = 1 ,1305.4  ,269,272.8,275.7
XS GIS Cut Line= 2
     2096317.637      382568.211     2095791.738      382734.657
#Sta/Elev= 27
       0 3113.01    20.1 3112.34    50.2 3111.67   110.3 3110.58   220.6 3108.36
   230.7  3108.1   240.7 3107.74     254 3107.14   260.8 3106.87     269  3106.9
   270.8  3106.9   280.8 3107.83   290.8 3109.44   300.9 3110.91   320.9 3113.27
     331 3114.74     341 3116.68     351  3119.1     361 3121.97   401.2 3133.92
   411.2 3137.01   421.2 3140.26   451.3 3150.77   471.4 3157.48   511.5 3171.37
   541.6 3182.35   551.6 3186.08
#Mann= 3 , 0 , 0
       0      .1       0     254    .045       0     269      .1       0
Bank Sta=254,269
XS Rating Curve= 0 ,0
Exp/Cntr=0.3,0.1

Type RM Length L Ch R = 1 ,1032.6  ,368.6,383.4,399
XS GIS Cut Line= 2
     2096162.443      382397.944     2095606.249      382475.168
#Sta/Elev= 30
       0 3102.05   110.3 3099.48   130.4  3098.5   140.4 3098.17   160.4 3098.21
   170.5 3098.02   220.6 3096.88     245 3096.19   250.7 3096.09     260  3097.5
   260.7 3097.61   270.7 3101.77   280.8 3107.15   290.8 3112.23   320.9 3126.65
   330.9 3131.71   340.9 3137.03     351 3142.85     361 3149.23     371 3155.85
     381 3162.27   421.2 3186.68   431.2 3192.89   441.2 3199.26   461.3 3212.86
   471.3 3219.38   491.3 3231.39   501.4 3237.26   521.4 3248.62   561.5 3271.17
#Mann= 3 , 0 , 0
       0      .1       0     245    .045       0     260      .1       0
Bank Sta=245,260
XS Rating Curve= 0 ,0
Exp/Cntr=0.3,0.1

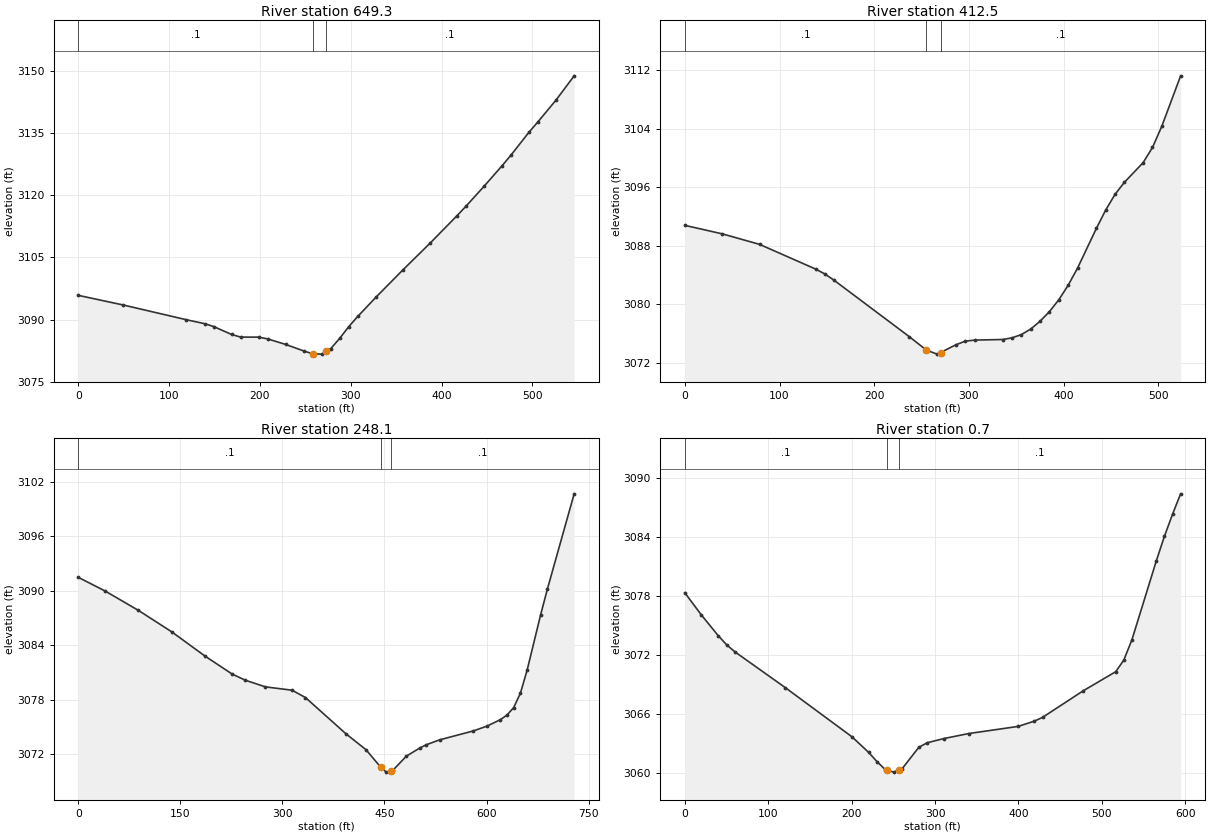
Type RM Length L Ch R = 1 ,649.3   ,245.6,236.8,227.9
XS GIS Cut Line= 2
      2096201.28      382205.642     2095736.573         381919.
#Sta/Elev= 30
       0 3095.86    49.6 3093.53   119.1 3089.98     139 3089.04   148.9 3088.35
   168.8 3086.43   178.7  3085.8   198.6 3085.79   208.5 3085.36   228.3 3084.03
   248.2 3082.46   258.1 3081.77     268 3081.69   273.1 3082.37     278 3083.02
   287.9 3085.52   297.8 3088.32   307.8  3090.8   327.6 3095.38   357.4    3102
   387.2 3108.41     417 3115.07   426.9 3117.36   446.7 3122.14   466.6 3127.11
   476.5  3129.7   496.4 3135.24   506.3 3137.75   526.2    3143     546  3148.8
#Mann= 3 , 0 , 0
       0      .1       0   258.1    .045       0   273.1      .1       0
Bank Sta=258.1,273.1
XS Rating Curve= 0 ,0
Exp/Cntr=0.3,0.1

Type RM Length L Ch R = 1 ,412.5   ,174.4,164.4,154.3
XS GIS Cut Line= 3
     2096346.917       381907.64     2096064.542      381861.544
     2095830.555       381901.61
#Sta/Elev= 30
       0 3090.78    39.5 3089.62    78.9 3088.18   138.1  3084.8     148 3084.12
   157.9 3083.24   236.8 3075.57   255.1 3073.71   266.4 3073.16   270.1 3073.38
   286.1 3074.43     296 3074.93   305.9 3075.08   335.6 3075.16   345.5 3075.39
   355.4 3075.84   365.2 3076.59   375.1 3077.66     385 3078.98   394.9  3080.6
   404.8 3082.59   414.7 3084.94   434.5 3090.35   444.4 3092.88   454.3 3095.03
   464.2 3096.68   483.9 3099.36   493.8 3101.44   503.7 3104.36   523.5 3111.24
#Mann= 3 , 0 , 0
       0      .1       0   255.1    .045       0   270.1      .1       0
Bank Sta=255.1,270.1
XS Rating Curve= 0 ,0
Exp/Cntr=0.3,0.1

Type RM Length L Ch R = 1 ,248.1   ,251.8,247.4,259.6
XS GIS Cut Line= 3
     2096420.198      381892.555      2096168.45      381673.203
     2095789.019      381782.554
#Sta/Elev= 30
       0 3091.46    39.3 3089.96    88.4 3087.82   137.5 3085.45   186.6 3082.77
   225.9 3080.82   245.5 3080.13     275  3079.4   314.3 3079.03   333.9 3078.22
   393.1 3074.25   422.8 3072.48   444.2 3070.58   452.4 3070.01   459.2 3070.14
   462.2  3070.2     482 3071.76   501.7 3072.66   511.6 3073.03   531.3 3073.57
   580.7 3074.55   600.4 3075.07   620.2 3075.78   630.1  3076.3   639.9 3077.12
   649.8  3078.7   659.7 3081.25   679.4  3087.3   689.3 3090.13   728.8 3100.66
#Mann= 3 , 0 , 0
       0      .1       0   444.2    .045       0   459.2      .1       0
Bank Sta=444.2,459.2
XS Rating Curve= 0 ,0
Exp/Cntr=0.3,0.1

Type RM Length L Ch R = 1 ,0.7     ,3.1,0.7,0
XS GIS Cut Line= 3
     2096216.531      381367.096     2095889.183      381518.781
     2095701.631      381658.243
#Sta/Elev= 29
       0 3078.31      20 3076.04    40.1 3073.95    50.1 3073.03    60.1 3072.31
   120.3 3068.69   200.4 3063.69   220.5  3062.1   230.5 3061.16   240.5 3060.35
   241.9 3060.32   250.5  3060.1   256.9 3060.32   260.6 3060.45   280.6 3062.62
   290.6 3063.08   310.7 3063.51   340.7 3064.02   399.7 3064.74   419.2 3065.28
     429 3065.66   477.6 3068.35   516.6 3070.29   526.3 3071.46   536.1 3073.53
   565.3 3081.53     575 3084.02   584.8 3086.28   594.5 3088.35
#Mann= 3 , 0 , 0
       0      .1       0   241.9    .045       0   256.9      .1       0
Bank Sta=241.9,256.9
XS Rating Curve= 0 ,0
Exp/Cntr=0.3,0.1

Chan Stop Cuts=-1
Use User Specified Reach Order=0